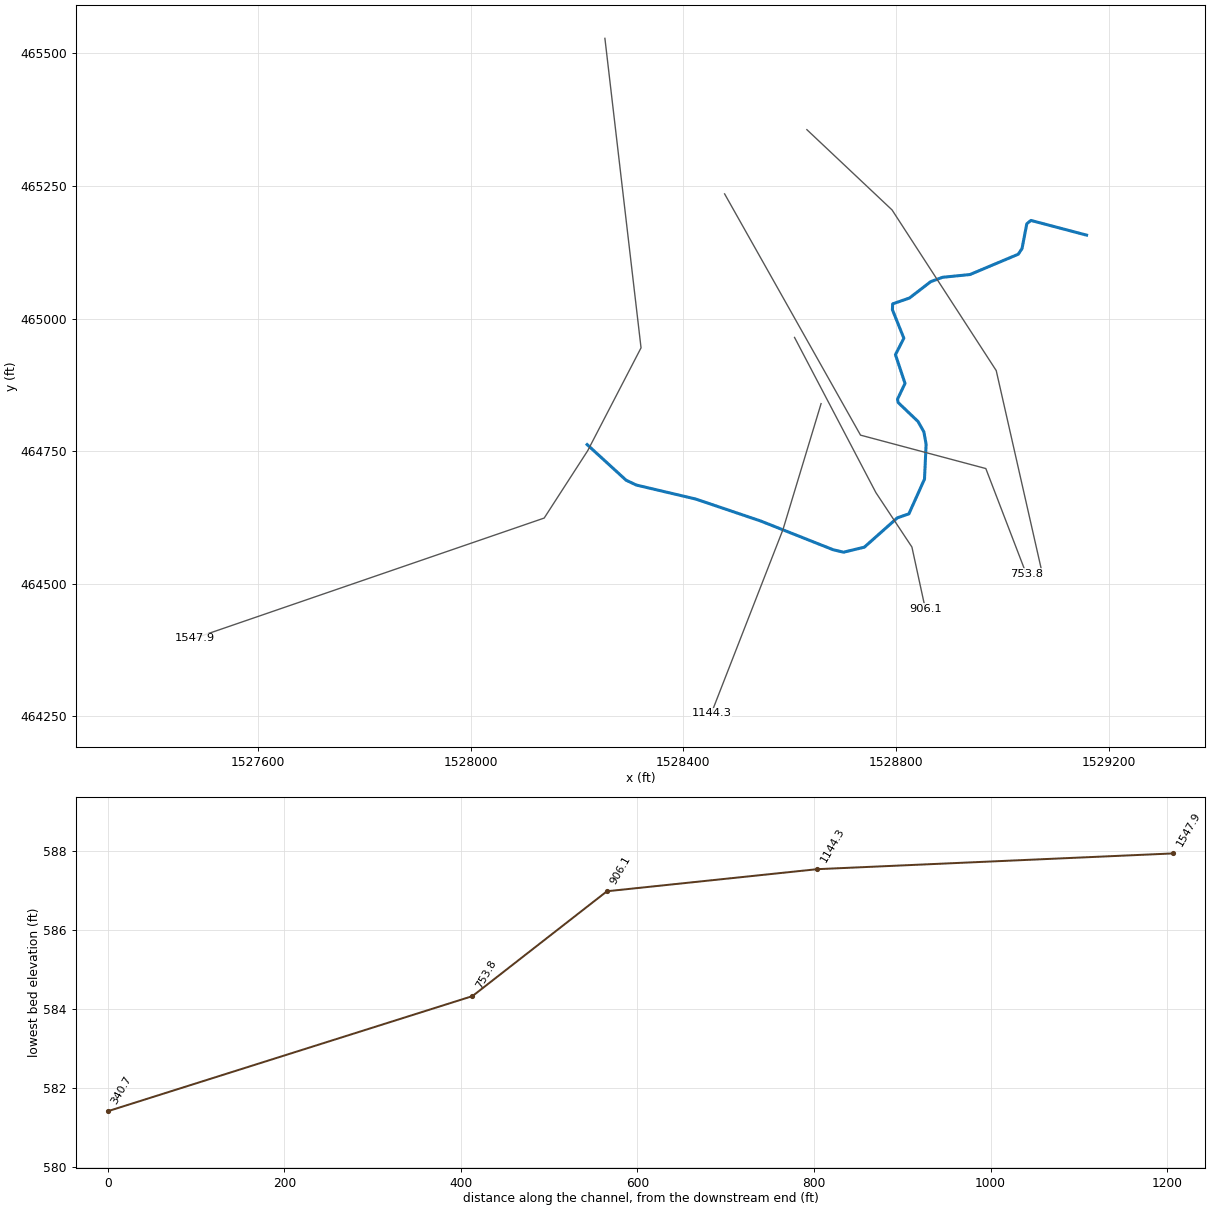
--- RCKLICKBR.prj (project) ---

Proj Title=RCKLICKBR
Current Plan=p01
Default Exp/Contr=0,0
English Units
Geom File=g01
Flow File=f01
Plan File=p01
BEGIN DESCRIPTION:
END DESCRIPTION:
DSS Export Rating Curves= 0
DSS Export Rating Curve Sorted= 0
DSS Export Volume Flow Curves= 0
DXF OffsetX= 0
DXF OffsetY= 0
DXF ScaleX= 0
DXF ScaleY= 0

--- RCKLICKBR.p01 (plan) ---

Plan Title=Floodplain
Program Version=4.00
Geom File=g01
Flow File=f01
K Sum by GR=0
Std Step Tol=0.01
Critical Tol=0.01
Num of Std Step Trials=20
Max Error Tol=0.3
Flow Tol Ratio=0.001
Split Flow NTrial=30
Split Flow Tol=0.02
Split Flow Ratio=0.02
Log Output Level=0
Friction Slope Method=1
Unsteady Friction Slope Method=2
Unsteady Bridges Friction Slope Method=1
Global Log Level=0
CheckData=False
Run HTab=0
Run UNet=0
Run PostProcess=0
UNET Theta=0
UNET Theta Warmup=0
UNET ZTol=0
UNET ZSATol=0
UNET MxIter=0
UNET MaxInSteps=0
UNET DtIC=0
UNET DtMin=0
UNET MaxCRTS=0
UNET WFStab=0
UNET SFStab=0
UNET WFX=0
UNET SFX=0
UNET DSS MLevel=0
UNET DZMax Abort=0
UNET Convert EG Bridges=0
UNET Use Existing IB Tables=0
UNET Froude Limit=0
UNET Froude Power=0
Write IC File=0
Echo Input=False
Echo Output=False
Write Detailed=0

--- RCKLICKBR.f01 (steady flow) ---

Flow Title=NFF Regression Equation
Program Version=4.00
Number of Profiles=1
Profile Names=P100yr
River Rch & RM=RCKLICKBR,Main      ,1547.9
     358
Boundary for River Rch & Prof#=RCKLICKBR,Main      ,1
Up Type=0
Dn Type=3
Dn Slope=0.00894

--- RCKLICKBR.g01 (geometry) ---

Geom Title=USGS 10m DEM
Program Version=4.00

River Reach=RCKLICKBR       ,Main
Reach XY= 30
      1528218.84      464762.308      1528292.05      464695.219
     1528311.249      464686.049     1528423.111      464659.654
     1528545.316      464618.254     1528681.654      464564.103
      1528701.36      464559.382     1528740.458       464568.87
     1528802.504      464624.137      1528824.29      464631.714
     1528853.627      464697.167     1528856.685      464762.811
     1528852.453      464786.325     1528841.511      464805.799
     1528804.029      464841.646     1528802.831      464847.833
     1528816.995      464877.698     1528798.973      464931.846
     1528814.793      464962.905     1528793.295      465016.438
     1528793.722      465027.665     1528825.481       465038.74
     1528865.413      465069.584      1528887.69      465077.764
     1528939.183      465082.957     1529030.068      465121.263
     1529037.177      465132.013     1529046.131      465178.693
     1529053.888      465184.976     1529158.604      465157.299

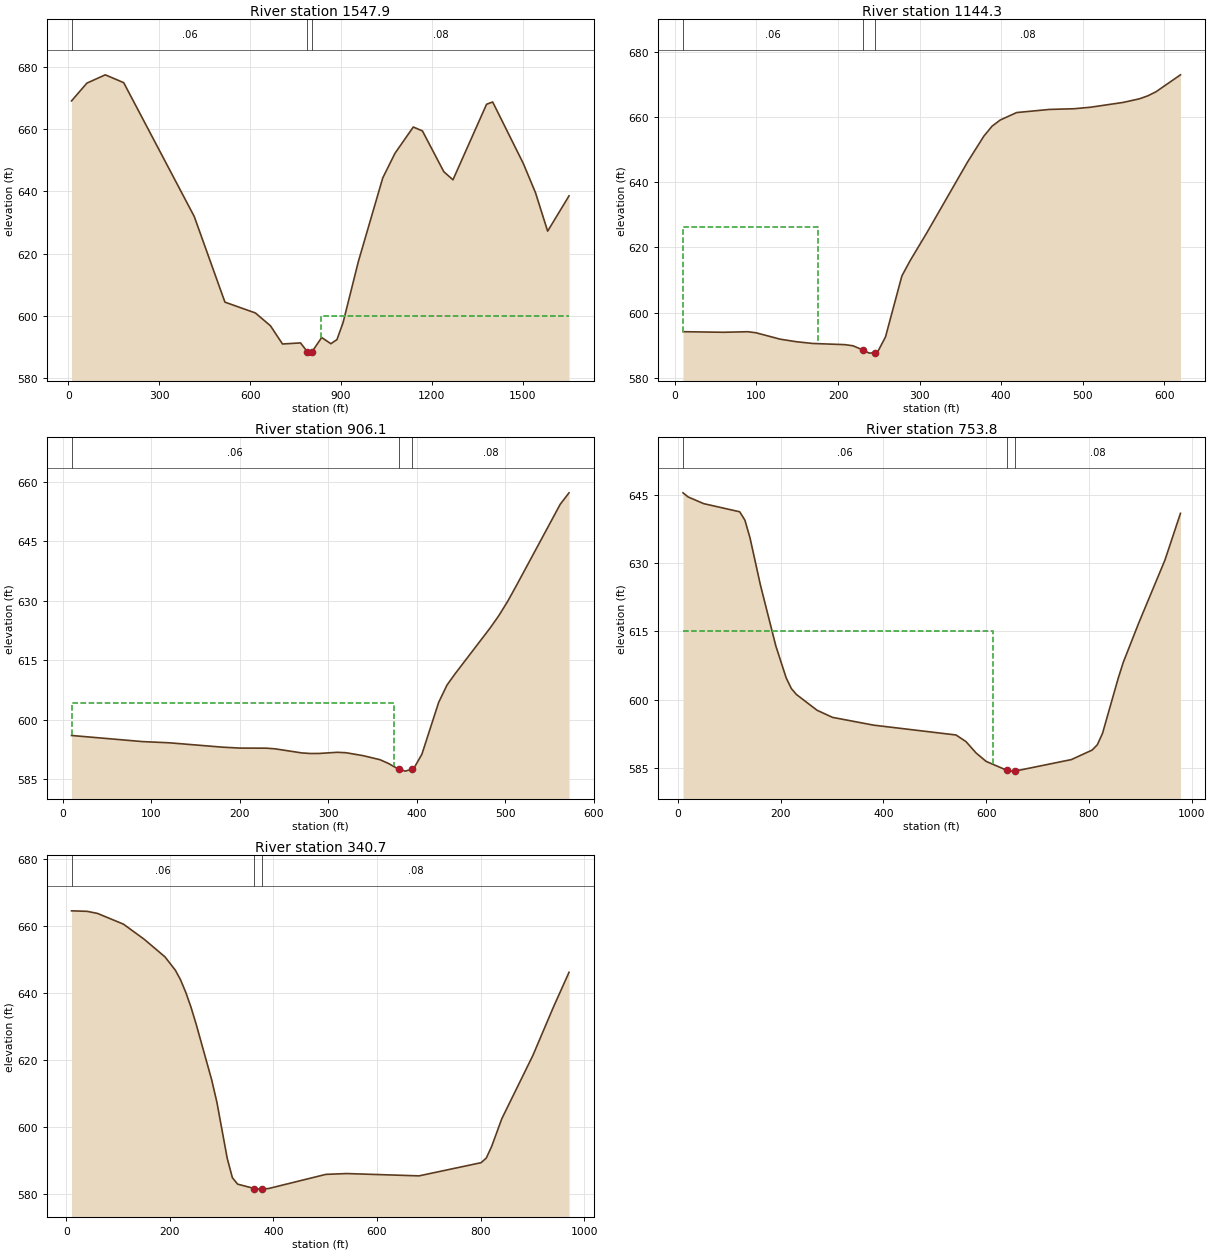
Type RM Length L Ch R = 1 ,1547.9  ,399.5,403.5,407.3
XS GIS Cut Line= 5
     1528252.256      465528.362     1528320.263      464944.759
     1528219.905      464750.842     1528138.011      464623.765
     1527480.276      464397.114
#Sta/Elev= 30
    10.1  669.12    60.8  674.84   121.6  677.51   182.3  674.99   415.3  631.92
   516.6  604.36   617.3  600.87     667  596.74   706.7  590.89   766.2  591.24
   788.5  588.42     796  587.95   803.5  588.29   836.1  592.98   866.4  590.98
   886.5   592.3   906.7  597.77   957.1  617.39  1037.7  644.32  1078.1  652.26
  1138.6  660.72  1168.8  659.45  1239.4  646.33  1269.6  643.73  1380.5  668.03
  1400.7  668.78  1501.5  649.05  1541.9  639.64  1582.2   627.2  1652.8  638.56
#Mann= 3 , 0 , 0
    10.1     .06       0   788.5    .045       0   803.5     .08       0
#XS Ineff= 2 , 0
                          834.39          599.87
Permanent Ineff=
       F       F
Bank Sta=788.5,803.5
XS Rating Curve= 0 ,0
Exp/Cntr=0.3,0.1

Type RM Length L Ch R = 1 ,1144.3  ,218.3,238.2,259.9
XS GIS Cut Line= 3
      1528659.03      464839.518     1528587.288      464601.923
      1528452.49      464255.471
#Sta/Elev= 30
     9.9  594.13    59.6  593.95    89.3  594.12    99.3   593.8   129.1  591.83
   148.9  591.05   168.8  590.52   208.5  590.15   218.4   589.8   230.8  588.49
   238.3  587.55   245.8  587.71   248.2  587.76   258.2  592.51   278.3  611.25
   288.4  615.92   308.5  624.32   358.7  646.16   378.8  654.14   388.9  657.21
   398.9  659.09     419  661.38   459.2  662.34   489.3  662.55   509.4  663.01
   549.6  664.49   569.7  665.61   579.8  666.51   589.8  667.75   619.9  672.96
#Mann= 3 , 0 , 0
     9.9     .06       0   230.8    .045       0   245.8     .08       0
#XS Ineff= 2 , 0
             175  626.15
Permanent Ineff=
       F       F
Bank Sta=230.8,245.8
XS Rating Curve= 0 ,0
Exp/Cntr=0.3,0.1

Type RM Length L Ch R = 1 ,906.1   ,135.1,152.4,169.7
XS GIS Cut Line= 4
      1528609.09      464964.359     1528762.159      464671.783
     1528829.975      464569.091     1528855.164      464452.835
#Sta/Elev= 30
      10  595.98    90.1  594.44   120.1  594.14   180.1  593.04   200.1   592.8
   230.1  592.78   240.1  592.61   270.2  591.58   280.2  591.43   290.2  591.45
   310.2  591.74   320.2  591.63   339.7  590.88   358.6  589.87   368.1  588.93
   377.5  587.74   379.5  587.58     387  586.99   394.5  587.45   396.5  587.57
   405.9  591.23   424.9  604.34   434.3  608.69   443.8  611.64     483  623.07
   492.9  626.21   502.8  629.78   512.7  633.77   562.3   654.3   572.2  657.17
#Mann= 3 , 0 , 0
      10     .06       0   379.5    .045       0   394.5     .08       0
#XS Ineff= 2 , 0
           374.1  604.09
Permanent Ineff=
       F       F
Bank Sta=379.5,394.5
XS Rating Curve= 0 ,0
Exp/Cntr=0.3,0.1

Type RM Length L Ch R = 1 ,753.8   ,432.4,413.1,381.5
XS GIS Cut Line= 4
     1528477.519      465235.039     1528733.259      464780.135
     1528969.034      464717.142      1529045.02       464518.85
#Sta/Elev= 30
      10  645.38    20.1  644.47    50.2  643.01   120.4  641.22   130.5  639.39
   140.5  635.48   160.6  625.21   190.7   611.8   210.8   604.8   220.8  602.46
   230.8  601.14     271  597.68   301.1  596.12   381.4  594.41   541.4  592.26
   560.9   590.8   580.4  588.32     600  586.47   641.3  584.47   648.8  584.33
   656.3  584.34   765.9  586.86   806.4  588.95   816.5  590.12   826.6  592.63
   856.9  604.63     867  608.21   897.4  616.92   947.9  630.58   978.3  640.88
#Mann= 3 , 0 , 0
      10     .06       0   641.3    .045       0   656.3     .08       0
#XS Ineff= 2 , 0
          614.21  615.13
Permanent Ineff=
       F       F
Bank Sta=641.3,656.3
XS Rating Curve= 0 ,0
Exp/Cntr=0.3,0.1

Type RM Length L Ch R = 1 ,340.7   ,362.1,340.7,315.6
XS GIS Cut Line= 4
     1528632.308      465356.151     1528792.642      465204.724
     1528988.606      464901.871     1529074.712      464521.819
#Sta/Elev= 30
      10  664.52    40.1  664.37    60.1  663.75   110.3  660.54   150.4  656.02
   190.5  650.77   210.5  646.79   220.5  643.94   230.6   640.2   240.6  635.81
   250.6  630.73   280.7  614.04   290.7   607.4   310.7  590.62   320.7  584.82
   330.8   582.9   363.3  581.58  370.84  581.41   378.3  581.43   390.9   581.6
   501.1  585.81   541.2  586.06   681.2  585.37   801.1  589.31   811.1   590.7
   821.1  594.02   841.1  602.45     901   621.3     941  635.86   970.9  646.16
#Mann= 3 , 0 , 0
      10     .06       0   363.3    .045       0   378.3     .08       0
Bank Sta=363.3,378.3
XS Rating Curve= 0 ,0
Exp/Cntr=0.3,0.1

Chan Stop Cuts=-1
Use User Specified Reach Order=0